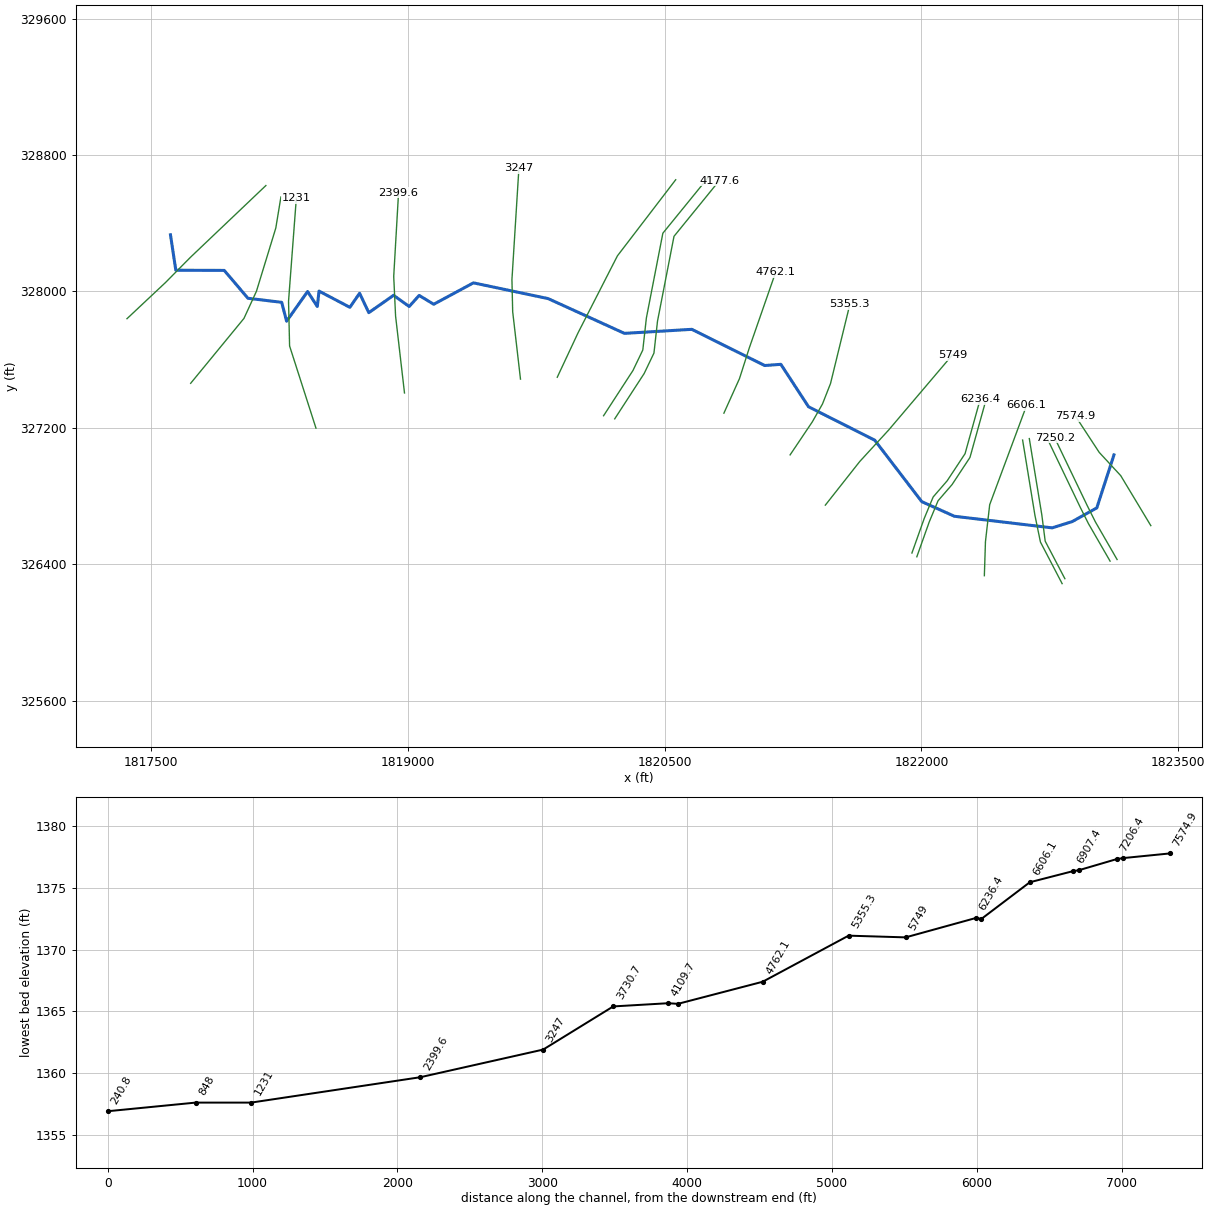
--- GladyCrk.prj (project) ---

Proj Title=GladyCrk
Current Plan=p01
Default Exp/Contr=0,0
English Units
Geom File=g01
Flow File=f01
Plan File=p01
BEGIN DESCRIPTION:
END DESCRIPTION:
DSS Export Rating Curves= 0
DSS Export Rating Curve Sorted= 0
DSS Export Volume Flow Curves= 0
DXF OffsetX= 0
DXF OffsetY= 0
DXF ScaleX= 0
DXF ScaleY= 0

--- GladyCrk.p01 (plan) ---

Plan Title=Floodplain
Program Version=4.00
Geom File=g01
Flow File=f01
K Sum by GR=0
Std Step Tol=0.01
Critical Tol=0.01
Num of Std Step Trials=20
Max Error Tol=0.3
Flow Tol Ratio=0.001
Split Flow NTrial=30
Split Flow Tol=0.02
Split Flow Ratio=0.02
Log Output Level=0
Friction Slope Method=1
Unsteady Friction Slope Method=2
Unsteady Bridges Friction Slope Method=1
Global Log Level=0
CheckData=False
Run HTab=0
Run UNet=0
Run PostProcess=0
UNET Theta=0
UNET Theta Warmup=0
UNET ZTol=0
UNET ZSATol=0
UNET MxIter=0
UNET MaxInSteps=0
UNET DtIC=0
UNET DtMin=0
UNET MaxCRTS=0
UNET WFStab=0
UNET SFStab=0
UNET WFX=0
UNET SFX=0
UNET DSS MLevel=0
UNET DZMax Abort=0
UNET Convert EG Bridges=0
UNET Use Existing IB Tables=0
UNET Froude Limit=0
UNET Froude Power=0
Write IC File=0
Echo Input=False
Echo Output=False
Write Detailed=0

--- GladyCrk.f01 (steady flow) ---

Flow Title=NFF Regression Equation
Program Version=4.00
Number of Profiles=1
Profile Names=P100yr
River Rch & RM=GladyCrk,Main      ,7574.9
     336
River Rch & RM=GladyCrk,Main      ,4177.6
     395
River Rch & RM=GladyCrk,Main      ,3247
     589
River Rch & RM=GladyCrk,Main      ,240.8
     630
Boundary for River Rch & Prof#=GladyCrk,Main      ,1
Up Type=0
Dn Type=3
Dn Slope=0.000846

--- GladyCrk.g01 (geometry) ---

Geom Title=USGS 10m DEM
Program Version=4.10

River Reach=GladyCrk        ,Main
Reach XY= 30
     1823125.298      327041.416     1823024.951      326730.652
     1822881.201      326650.444     1822764.187      326613.638
     1822192.659      326681.694     1822002.034      326767.458
     1821727.034      327127.874     1821340.286      327323.881
     1821178.698      327572.536     1821084.253      327565.591
     1820658.212      327777.744     1820264.809      327754.133
     1819818.605      327957.952     1819382.255      328050.325
     1819150.038      327924.799     1819064.928      327976.583
     1819006.531      327911.556     1818915.575      327977.332
     1818770.594      327875.537      1818716.91      327989.323
     1818659.961      327906.905     1818479.873      328001.954
     1818469.688      327911.809     1818412.966      327999.594
     1818290.226      327825.351     1818261.676      327936.114
     1818064.428      327959.952      1817925.95      328123.292
     1817642.922      328124.306     1817611.645      328332.158

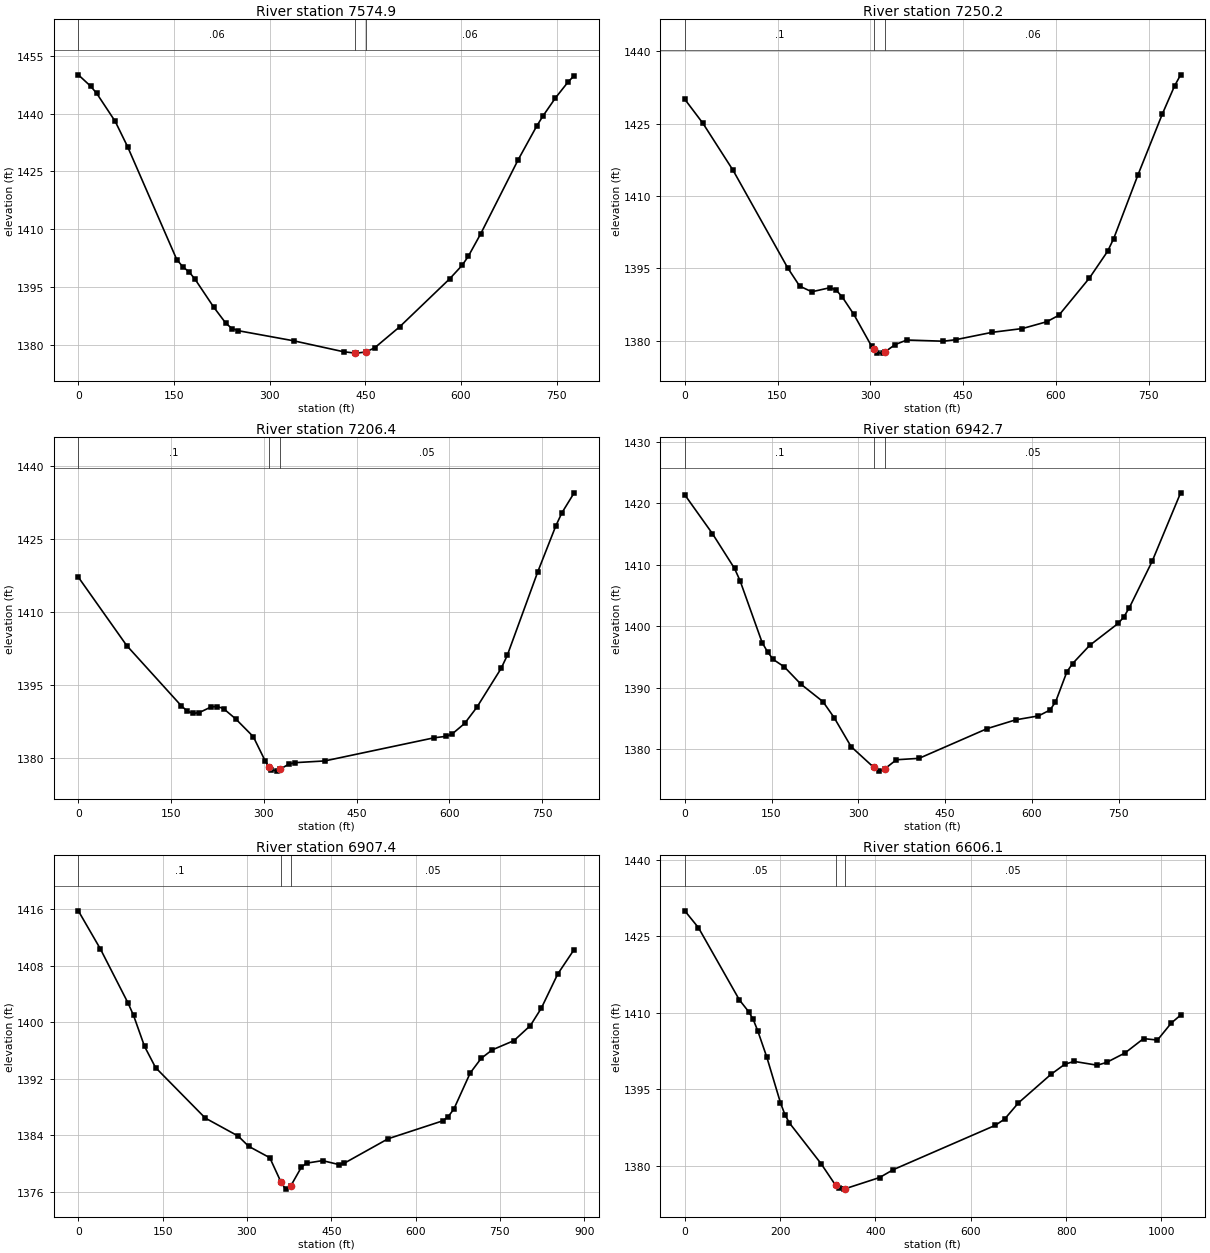
Type RM Length L Ch R = 1 ,7574.9  ,325.7,324.7,321.6
XS GIS Cut Line= 4
     1823340.633       326626.76     1823164.852      326919.729
     1823038.984      327056.448     1822900.095      327269.121
#Sta/Elev= 30
       0 1450.05    19.3  1447.1    28.9 1445.21    57.9 1437.94    77.2 1431.41
   154.3 1402.11     164 1400.18   173.6 1398.92   183.2 1396.94   212.2 1389.76
   231.5 1385.52   241.1 1384.18   250.8 1383.63   337.6 1381.01   415.8 1378.17
  434.28 1377.82   435.4 1377.81   450.6 1378.09   464.7  1379.2   503.8 1384.64
     582 1397.06   601.6 1400.57   611.3 1402.91   630.9 1408.79   689.5 1427.97
   718.8 1436.78   728.6 1439.39   748.1 1444.06   767.6 1448.14   777.4 1449.84
#Mann= 3 , 0 , 0
       0     .06       0  434.28    .045       0   450.6     .06       0
Bank Sta=434.28,450.6
XS Rating Curve= 0 ,0
Exp/Cntr=0.3,0.1

Type RM Length L Ch R = 1 ,7250.2  ,42.7,43.8,43.6
XS GIS Cut Line= 4
     1823143.585      326427.975     1823016.849      326648.462
     1822969.974      326742.212     1822779.001      327141.517
#Sta/Elev= 30
       0 1430.07    29.3 1425.09    78.2 1415.31   166.3 1395.13   185.8 1391.32
   205.4 1390.15   234.8    1391   244.5 1390.54   254.3 1389.13   273.4 1385.45
     302 1378.87   306.3 1378.24   311.5 1377.48     321 1377.43  323.26 1377.64
   340.1  1379.2   359.1 1380.15   418.2  1379.9   437.8 1380.21   496.8 1381.74
     546 1382.53   585.4 1383.94     605 1385.29   654.2 1392.98   683.7 1398.54
   693.6 1401.19   732.9 1414.42   772.2 1427.01   791.9 1432.81   801.8 1435.14
#Mann= 3 , 0 , 0
       0      .1       0   306.3    .045       0  323.26     .06       0
Bank Sta=306.3,323.26
XS Rating Curve= 0 ,0
Exp/Cntr=0.3,0.1

Type RM Length L Ch R = 1 ,7206.4  ,271.5,263.7,255.4
XS GIS Cut Line= 4
     1823102.569      326418.644     1822975.833       326639.13
     1822928.958       326732.88     1822737.986      327132.186
#Sta/Elev= 30
       0 1417.12    78.2  1403.1   166.3 1390.77   176.1 1389.65   185.8 1389.17
   195.6 1389.36   215.2 1390.54     225 1390.59   234.8 1390.16   254.3 1388.08
   282.9 1384.42     302 1379.48   308.5 1378.24   311.5 1377.67     321 1377.35
  326.23 1377.74   340.1 1378.76   349.6 1379.08   398.5 1379.44   575.5 1384.19
   595.2 1384.49     605 1385.02   624.7 1387.13   644.4 1390.43   683.7 1398.41
   693.6 1401.07   742.7 1418.13   772.2 1427.65   782.1 1430.34   801.8 1434.41
#Mann= 3 , 0 , 0
       0      .1       0   308.5    .045       0  326.23     .05       0
Bank Sta=308.5,326.23
XS Rating Curve= 0 ,0
Exp/Cntr=0.3,0.1

Type RM Length L Ch R = 1 ,6942.7  ,33.9,35.3,37.3
XS GIS Cut Line= 4
     1822838.463      326315.562     1822723.446      326535.614
     1822703.481      326690.996     1822630.564      327137.177
#Sta/Elev= 30
       0 1421.36    47.8 1415.05      86 1409.39    95.5 1407.41   133.7 1397.34
   143.2 1395.81   152.8  1394.6   171.9  1393.4   200.6 1390.59   238.8 1387.74
   258.1 1385.15   287.5 1380.42   326.6 1377.05   336.4 1376.44   346.2 1376.85
   365.8 1378.29     405 1378.52   522.9 1383.36     572 1384.78   611.4 1385.42
     631 1386.36   640.8 1387.66   660.5 1392.59   670.3 1393.92   699.8 1396.88
     749 1400.45   758.8 1401.49   768.6 1403.04   807.9 1410.56   857.1 1421.69
#Mann= 3 , 0 , 0
       0      .1       0   326.6    .045       0   346.2     .05       0
Bank Sta=326.6,346.2
XS Rating Curve= 0 ,0
Exp/Cntr=0.3,0.1

Type RM Length L Ch R = 1 ,6907.4  ,307.5,301.2,293.2
XS GIS Cut Line= 4
     1822822.404      326286.482     1822695.668      326530.406
      1822663.55      326686.656     1822591.501      327128.496
#Sta/Elev= 30
       0 1415.81    39.3  1410.4    88.4 1402.75    98.2    1401   117.8  1396.6
   137.4  1393.6   225.8 1386.45   284.3  1383.9     303 1382.45   340.6 1380.83
   360.7 1377.35   368.7 1376.38   378.1 1376.86   396.9  1379.5   406.2 1380.06
   434.4 1380.42   463.6 1379.86   473.3 1380.06   551.2 1383.52   648.5 1386.06
   658.2 1386.67     668 1387.71   697.2 1392.84   716.6  1394.9   736.1  1396.1
     775 1397.42   804.2 1399.55   823.7 1402.02   852.9 1406.86   882.1 1410.33
#Mann= 3 , 0 , 0
       0      .1       0   360.7    .045       0   378.1     .05       0
Bank Sta=360.7,378.1
XS Rating Curve= 0 ,0
Exp/Cntr=0.3,0.1

Type RM Length L Ch R = 1 ,6606.1  ,333.9,334.8,327.6
XS GIS Cut Line= 4
     1822367.847      326333.005     1822374.357      326533.526
     1822399.097      326749.671     1822615.243      327333.005
#Sta/Elev= 30
       0 1429.98    28.7 1426.67   114.6 1412.52   133.8 1410.25   143.3 1408.75
   152.9 1406.52     172 1401.34   200.6 1392.42   210.1 1390.05   219.5 1388.43
   285.8 1380.47   316.2 1376.25   323.6 1375.63     333 1375.47  335.89 1375.53
   408.7 1377.74   437.6 1379.29   651.5 1387.97   670.9 1389.18   700.1 1392.37
   768.1 1397.94   797.3 1399.93   816.7 1400.49   865.3 1399.74   884.8 1400.28
   923.6 1402.14   962.5 1404.95   991.7 1404.67  1020.8 1408.01  1040.3 1409.55
#Mann= 3 , 0 , 0
       0     .05       0   316.2    .045       0  335.89     .05       0
Bank Sta=316.2,335.89
XS Rating Curve= 0 ,0
Exp/Cntr=0.3,0.1

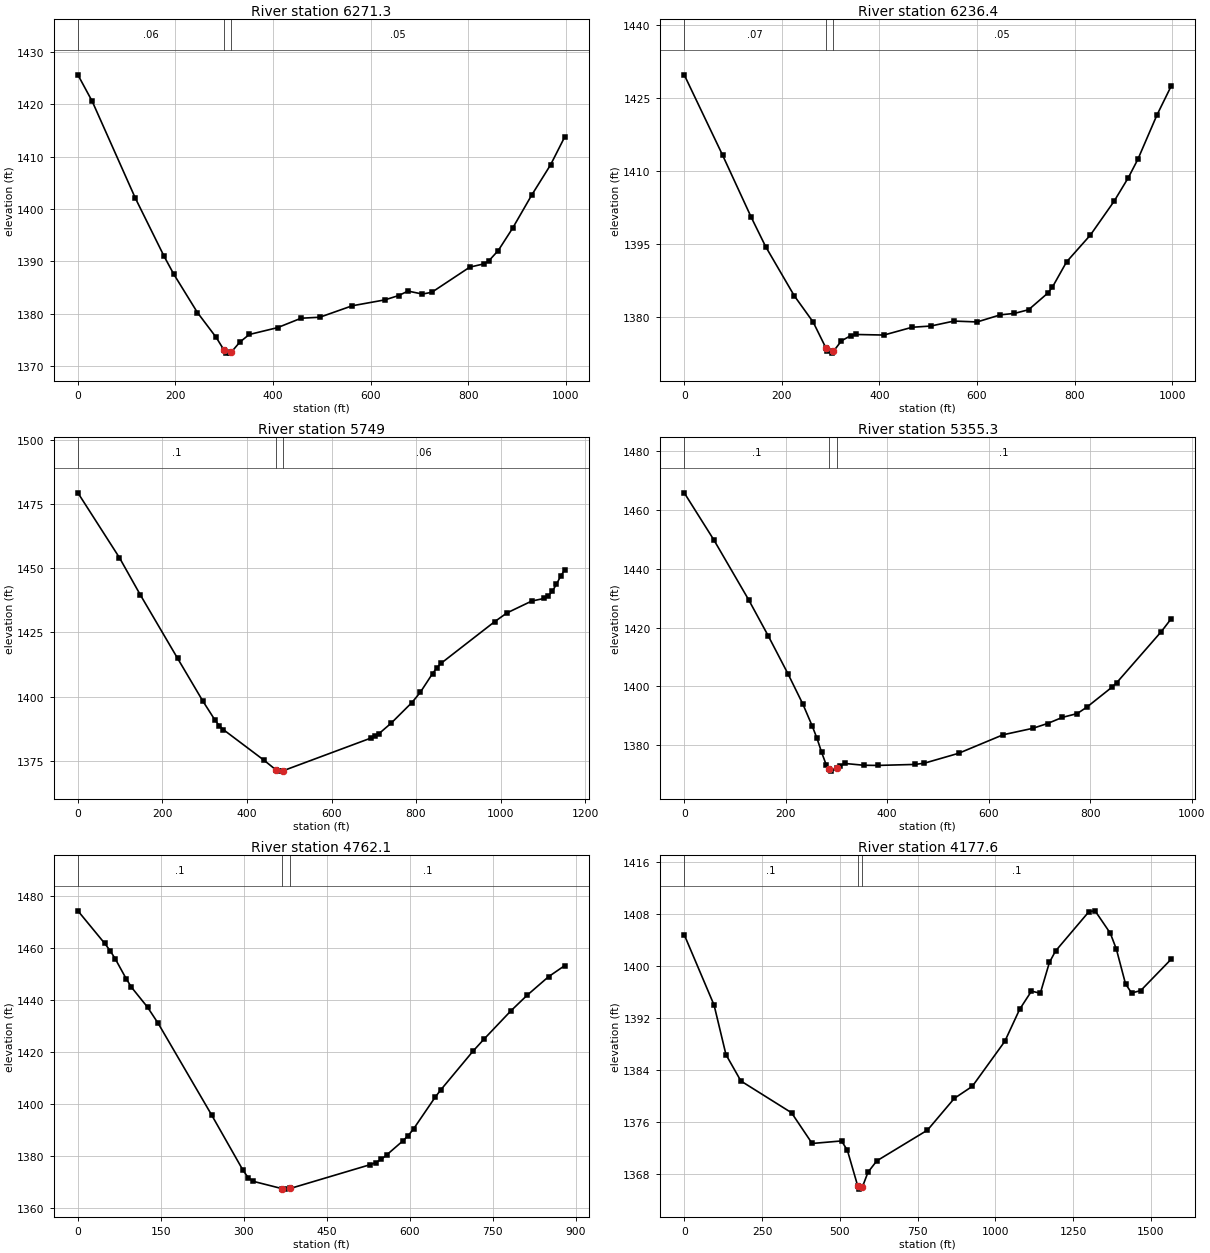
Type RM Length L Ch R = 1 ,6271.3  ,35,35,35
XS GIS Cut Line= 6
     1821973.272      326444.035     1822045.494      326647.594
     1822097.317      326772.594     1822179.349      326867.646
     1822283.776        327026.5     1822372.317       327345.51
#Sta/Elev= 30
       0 1425.67    29.4  1420.6   117.8  1402.1   176.7    1391   196.4  1387.6
     245 1380.25   283.6 1375.48   299.2 1373.12     303 1372.58   312.6 1372.49
   314.2 1372.65     332  1374.6   351.3 1376.05   409.3 1377.36   457.6 1379.16
   495.9 1379.35   562.4 1381.54     629 1382.66   657.5 1383.49   676.7 1384.35
   705.9 1383.78   725.4 1384.11   803.3 1388.92   832.5 1389.55   842.2 1390.11
   861.7  1392.1   890.9 1396.33   929.9 1402.64   968.8 1408.45     998 1413.82
#Mann= 3 , 0 , 0
       0     .06       0   299.2    .045       0   314.2     .05       0
Bank Sta=299.2,314.2
XS Rating Curve= 0 ,0
Exp/Cntr=0.3,0.1

Type RM Length L Ch R = 1 ,6236.4  ,494.7,487.4,478.8
XS GIS Cut Line= 6
     1821944.626       326466.17     1822016.849      326669.729
     1822068.672      326794.729     1822150.703      326889.781
      1822255.13      327048.635     1822343.672      327367.646
#Sta/Elev= 30
       0  1429.7    78.5 1413.24   137.4 1400.45   166.9 1394.44   225.7 1384.33
   264.3 1378.95   290.7 1373.58   293.3 1373.05     303 1372.58   305.7 1372.93
   322.3 1375.11   341.6 1376.18   351.3 1376.41   409.3 1376.29   467.2 1377.89
   505.4 1378.14   552.9 1379.16   600.4 1378.98     648 1380.44   676.7 1380.73
   705.9 1381.49   744.9 1384.87   754.6 1386.11   783.8 1391.32   832.5 1396.81
   881.2 1403.76   910.4 1408.61   929.9 1412.37   968.8 1421.41     998 1427.36
#Mann= 3 , 0 , 0
       0     .07       0   290.7    .045       0   305.7     .05       0
Bank Sta=290.7,305.7
XS Rating Curve= 0 ,0
Exp/Cntr=0.3,0.1

Type RM Length L Ch R = 1 ,5749    ,388.2,393.7,398.4
XS GIS Cut Line= 4
     1821438.724      326747.073     1821639.244      327002.281
     1821808.515      327187.177     1822180.911      327627.281
#Sta/Elev= 30
       0  1479.3    98.4 1454.03   147.5 1439.65     236 1414.85   295.1  1398.4
   324.6 1390.79   334.2 1388.73   343.8 1387.19   440.3 1375.24   469.2  1371.4
   478.8    1371   485.6 1371.15   692.5 1383.82   702.3 1384.49     712 1385.54
   741.4 1389.71   790.2 1397.69   809.8  1401.6   839.1 1408.98   848.8 1411.11
   858.6 1412.89   985.6 1429.12    1015 1432.56  1073.6 1437.18  1102.9  1438.2
  1112.7 1439.15  1122.4 1441.01  1132.2 1443.74    1142 1446.86  1151.8 1449.36
#Mann= 3 , 0 , 0
       0      .1       0   469.2    .045       0   485.6     .06       0
Bank Sta=469.2,485.6
XS Rating Curve= 0 ,0
Exp/Cntr=0.3,0.1

Type RM Length L Ch R = 1 ,5355.3  ,586.3,593.2,598.2
XS GIS Cut Line= 5
     1821232.809      327041.663     1821363.018      327236.108
     1821422.046      327340.274     1821468.921      327460.066
     1821581.768      327923.608
#Sta/Elev= 30
       0 1465.82    58.5 1449.77   126.8 1429.48   165.8 1417.08   204.8 1404.13
     234 1393.86   252.4 1386.42   261.6 1382.31   270.8 1377.52   280.1 1373.14
   286.1 1371.84   289.3 1371.14   301.1 1372.05   307.7 1373.02   316.9 1373.74
   353.7 1373.14   381.3 1373.08   454.8 1373.42   473.2 1373.84   540.8 1377.21
   628.4 1383.51   686.8  1385.7     716 1387.34   745.3 1389.43   774.5 1390.72
   793.9 1392.97   842.6 1399.65   852.4 1401.25     940 1418.57   959.5 1422.94
#Mann= 3 , 0 , 0
       0      .1       0   286.1    .045       0   301.1      .1       0
Bank Sta=286.1,301.1
XS Rating Curve= 0 ,0
Exp/Cntr=0.3,0.1

Type RM Length L Ch R = 1 ,4762.1  ,580.3,584.5,587.4
XS GIS Cut Line= 4
     1820845.842      327286.135     1820936.988       327489.26
     1820994.279      327668.948     1821147.925      328111.656
#Sta/Elev= 30
       0 1474.19    48.4  1461.7    58.1 1458.95    67.8 1455.66    87.1 1448.21
    96.8 1444.87   125.8 1437.23   145.2 1430.97   241.5 1395.92   298.1 1374.74
   307.5 1371.85   316.9 1370.39   368.7  1367.6   373.5  1367.4   383.7 1367.65
   528.4  1376.8   538.2 1377.56   547.9 1378.79   557.7 1380.47     587 1385.86
   596.7 1387.89   606.5 1390.48   645.5 1402.64   655.3 1405.37   713.9 1420.32
   733.4 1424.85   782.2 1435.76   811.5 1441.74   850.6 1448.93   879.8 1453.18
#Mann= 3 , 0 , 0
       0      .1       0   368.7    .045       0   383.7      .1       0
Bank Sta=368.7,383.7
XS Rating Curve= 0 ,0
Exp/Cntr=0.3,0.1

Type RM Length L Ch R = 1 ,4177.6  ,67.8,67.9,67.8
XS GIS Cut Line= 6
     1820207.864      327252.932     1820379.739      327518.557
     1820437.031      327638.349     1820457.864      327825.849
     1820554.218      328323.245     1820819.051      328649.819
#Sta/Elev= 30
       0 1404.84    95.9 1393.99   134.2 1386.34   182.2 1382.28   344.8 1377.39
   411.2 1372.65   505.8 1373.04   524.6 1371.57   557.5 1366.12   562.4 1365.61
   572.5 1365.92   590.7 1368.22     619 1369.97   781.9 1374.71   868.3 1379.61
     926 1381.46  1030.5  1388.4    1078 1393.32  1116.1 1396.14  1144.6 1395.81
  1173.9 1400.58  1193.5 1402.32    1301  1408.4  1320.6 1408.52  1369.5 1405.07
    1389 1402.62  1418.4 1397.27  1437.9 1395.85  1467.3 1396.22    1565 1401.05
#Mann= 3 , 0 , 0
       0      .1       0   557.5    .045       0   572.5      .1       0
Bank Sta=557.5,572.5
XS Rating Curve= 0 ,0
Exp/Cntr=0.3,0.1

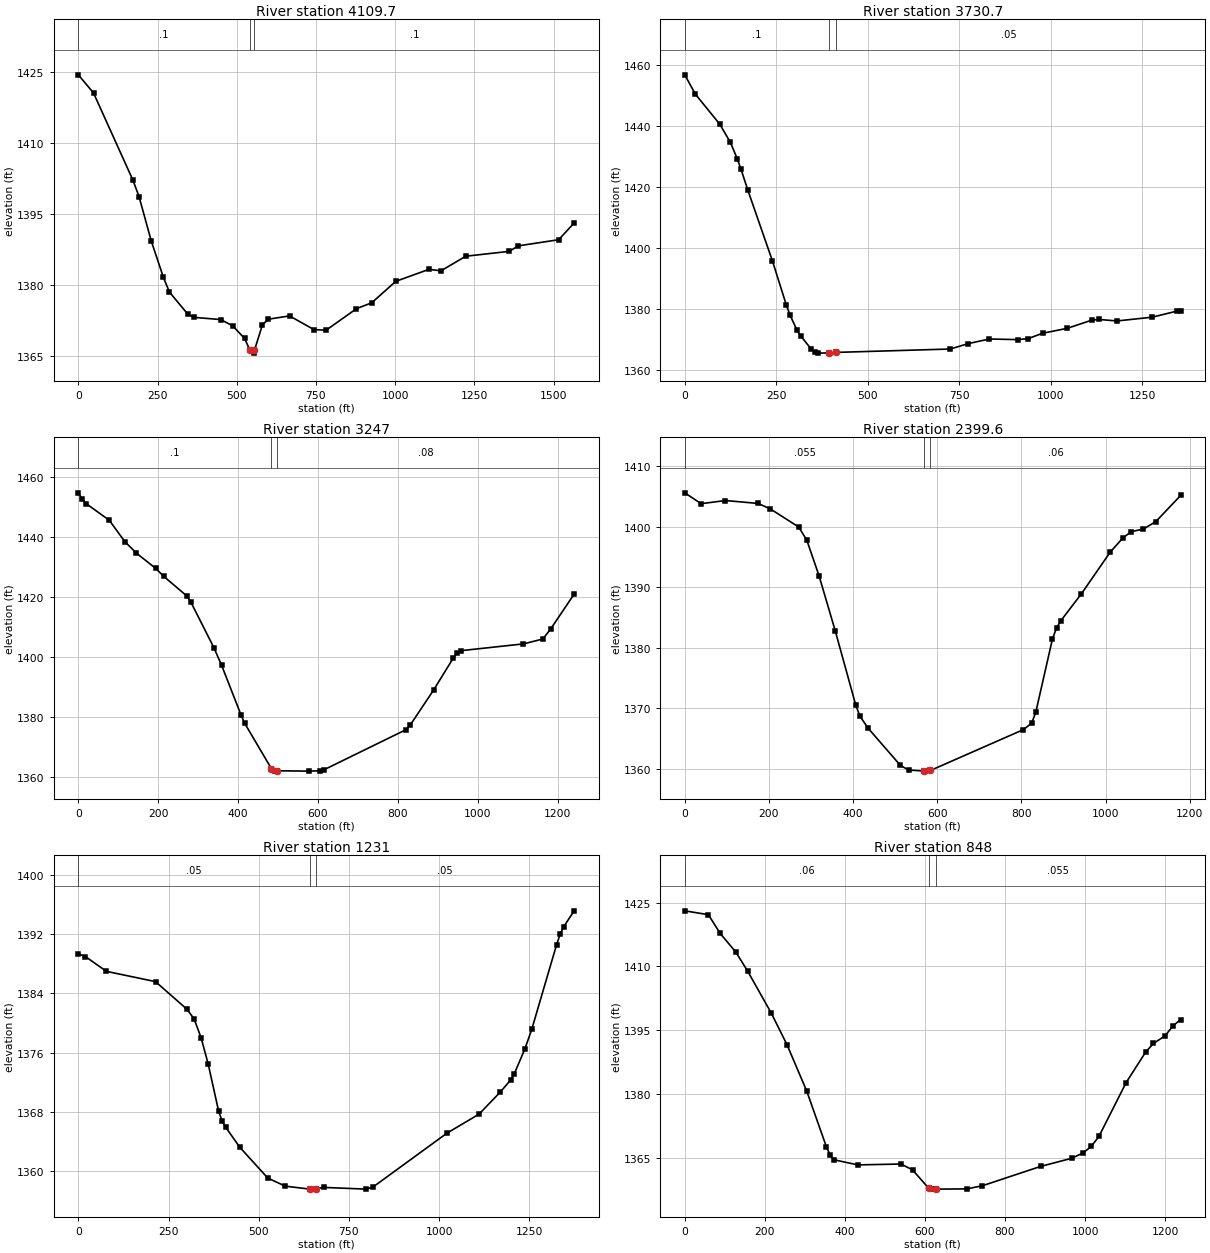
Type RM Length L Ch R = 1 ,4109.7  ,382.7,379,378
XS GIS Cut Line= 6
      1820142.76      327271.161     1820314.635      327536.786
     1820371.927      327656.578      1820392.76      327844.078
     1820489.114      328341.474     1820753.946      328668.048
#Sta/Elev= 30
       0 1424.36    47.9 1420.54   172.6  1402.1   191.8 1398.63   230.1 1389.33
   268.4 1381.66   287.6 1378.53   344.8 1373.94   363.8 1373.21   449.2 1372.74
   486.9 1371.43   524.6 1368.77     541 1366.38   552.9 1365.66     556 1366.27
   581.2 1371.67   600.1 1372.82   666.6 1373.51   743.5 1370.63   781.9 1370.49
   877.9 1375.03     926 1376.28    1002  1380.8  1106.6 1383.33  1144.6 1383.02
  1222.8  1386.1  1359.7 1387.12    1389 1388.29  1516.2 1389.58    1565 1393.12
#Mann= 3 , 0 , 0
       0      .1       0     541    .045       0     556      .1       0
Bank Sta=541,556
XS Rating Curve= 0 ,0
Exp/Cntr=0.3,0.1

Type RM Length L Ch R = 1 ,3730.7  ,472.9,483.7,488.2
XS GIS Cut Line= 4
     1819871.927      327496.689     1819993.455      327757.106
     1820223.489      328208.495     1820564.114      328654.849
#Sta/Elev= 30
       0 1456.68    28.7 1450.37    95.8 1440.45   124.5 1434.55   143.7 1429.07
   153.3 1425.84   172.4 1418.83   239.5 1395.68   277.8  1381.1   287.4 1377.97
   306.9 1372.85   316.6 1371.08   345.8  1366.7   355.6 1365.66   365.3  1365.4
   394.6 1365.47     414 1365.64   725.8 1366.75   774.5 1368.51   832.7 1370.04
   910.2 1369.83   939.2 1370.18   977.9 1371.91  1045.7 1373.54  1113.5 1376.25
  1132.8 1376.44  1181.2 1375.95    1278 1377.19  1345.8  1379.2  1355.5 1379.11
#Mann= 3 , 0 , 0
       0      .1       0   394.6    .045       0     414     .05       0
Bank Sta=394.6,414
XS Rating Curve= 0 ,0
Exp/Cntr=0.3,0.1

Type RM Length L Ch R = 1 ,3247    ,846.3,847.3,819.5
XS GIS Cut Line= 4
     1819657.083      327486.005      1819611.51       327880.97
      1819607.17      328069.772     1819647.991      328723.478
#Sta/Elev= 30
       0 1454.69     9.7 1452.51    19.4 1451.11    77.6 1445.53   116.4 1438.42
   145.5 1434.58   193.9 1429.47   213.3  1426.9   271.5 1420.31   281.2  1418.4
   339.4 1403.06   358.8 1397.17     407 1380.74   416.5 1377.85   483.6 1362.68
     492 1362.05   498.6 1362.01     577  1361.9     606 1362.02   615.8  1362.4
   821.1 1375.77   830.8 1377.22   889.5 1388.95   938.4 1399.51   948.1 1401.28
   957.9 1402.06  1114.3 1404.32  1163.2 1405.96  1182.8 1409.34  1241.4 1420.92
#Mann= 3 , 0 , 0
       0      .1       0   483.6    .045       0   498.6     .08       0
Bank Sta=483.6,498.6
XS Rating Curve= 0 ,0
Exp/Cntr=0.3,0.1

Type RM Length L Ch R = 1 ,2399.6  ,982.9,1168.7,1155.8
XS GIS Cut Line= 4
      1818979.24      327404.625     1818927.157      327856.014
     1818916.306      328088.219     1818944.518       328578.67
#Sta/Elev= 30
       0 1405.56    38.7 1403.77    96.7 1404.29     174 1403.81     203 1402.92
   270.7 1399.92     290 1397.73     319 1391.87   357.7 1382.74     406  1370.6
   415.7 1368.78     435 1366.78   512.5 1360.59   531.9 1359.84   568.7 1359.68
   570.6 1359.66   583.7 1359.77   804.7 1366.51   824.4 1367.59   834.2 1369.45
   873.5 1381.45   883.4 1383.31   893.2 1384.44   942.3  1388.9  1011.1 1395.81
  1040.6 1398.09  1060.2 1399.14  1089.7 1399.59  1119.2 1400.82  1178.1 1405.12
#Mann= 3 , 0 , 0
       0    .055       0   568.7    .045       0   583.7     .06       0
Bank Sta=568.7,583.7
XS Rating Curve= 0 ,0
Exp/Cntr=0.3,0.1

Type RM Length L Ch R = 1 ,1231    ,338.5,383,355.1
XS GIS Cut Line= 4
     1818461.879      327198.462     1818307.799      327680.232
      1818301.65      327942.819     1818347.223      328547.203
#Sta/Elev= 30
       0 1389.33    19.4 1388.97    77.8 1386.97     214 1385.58   301.5 1381.84
     321 1380.55   340.4 1378.01   359.9 1374.49   389.1 1368.08   398.8 1366.76
   408.5 1365.95   447.4 1363.26   525.3 1359.09   573.9    1358     642  1357.6
   658.2 1357.66   680.9 1357.83   797.8  1357.6   817.4  1357.9  1022.6 1365.17
  1110.6  1367.7  1169.3 1370.66  1198.6 1372.32  1208.4 1373.13  1237.7 1376.47
  1257.3 1379.19  1325.7 1390.53  1335.5 1391.95  1345.2 1392.96  1374.6 1395.13
#Mann= 3 , 0 , 0
       0     .05       0     642    .045       0   658.2     .05       0
Bank Sta=642,658.2
XS Rating Curve= 0 ,0
Exp/Cntr=0.3,0.1

Type RM Length L Ch R = 1 ,848     ,610,607.1,596.2
XS GIS Cut Line= 5
     1817729.775      327461.395     1818040.973      327841.604
     1818113.889      328000.458     1818227.171      328371.552
     1818257.118      328553.843
#Sta/Elev= 30
       0 1423.08      59 1422.17    88.4 1417.76   127.8 1413.33   157.2 1408.86
   216.2 1398.99   255.5 1391.55   304.6 1380.68   353.8 1367.55   363.6 1365.54
   373.4 1364.49   432.4  1363.3   539.9 1363.51     569 1362.13   609.4  1357.8
   617.6  1357.6   627.3  1357.6   704.9 1357.66   743.7  1358.4   889.2 1362.95
   966.8 1364.86   995.9 1366.16  1015.3 1367.64  1034.7    1370  1102.7 1382.68
  1151.4 1389.84  1170.8 1391.88    1200 1393.66  1219.4 1395.98  1238.8 1397.51
#Mann= 3 , 0 , 0
       0     .06       0   609.4    .045       0   627.3    .055       0
Bank Sta=609.4,627.3
XS Rating Curve= 0 ,0
Exp/Cntr=0.3,0.1

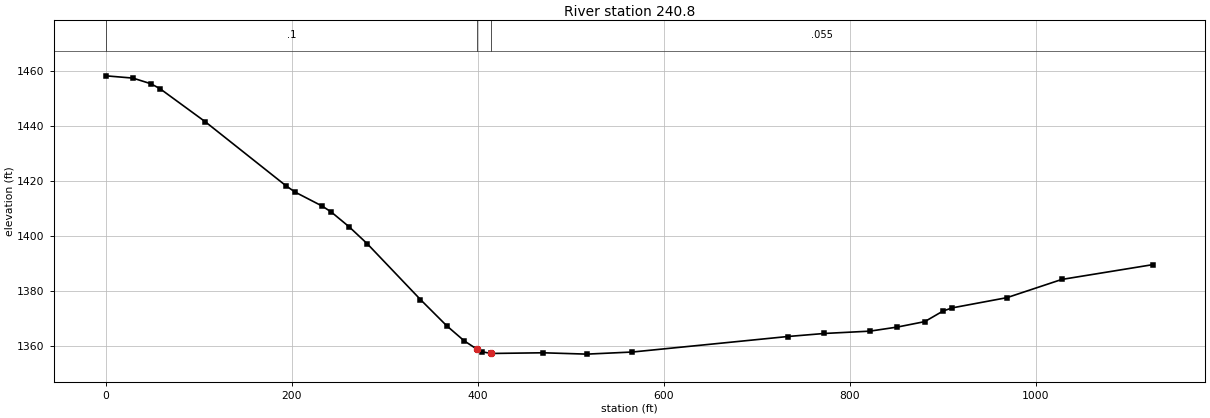
Type RM Length L Ch R = 1 ,240.8   ,244.7,240.8,236.1
XS GIS Cut Line= 4
     1817357.532      327840.172     1817583.226      328052.845
     1817728.625      328200.415     1818169.272      328620.988
#Sta/Elev= 30
       0 1458.37    29.1 1457.54    48.4 1455.48    58.2 1453.68   106.6  1441.7
   193.8 1418.26   203.5 1415.98   232.6 1410.89   242.3 1408.75   261.7 1403.31
     281 1397.19   338.4 1376.78   366.6 1367.24   385.4 1361.75   399.2 1358.69
   404.3 1357.79   414.2 1357.14   470.2 1357.39   517.3  1356.9   566.4 1357.67
   733.4 1363.32   772.7 1364.43   821.8 1365.28   851.3 1366.77   880.8 1368.75
   900.4  1372.6   910.3 1373.76   969.2 1377.49  1028.2 1384.13  1126.4 1389.54
#Mann= 3 , 0 , 0
       0      .1       0   399.2    .045       0   414.2    .055       0
Bank Sta=399.2,414.2
XS Rating Curve= 0 ,0
Exp/Cntr=0.3,0.1

Chan Stop Cuts=-1
Use User Specified Reach Order=0
Composite Channel Slope=5